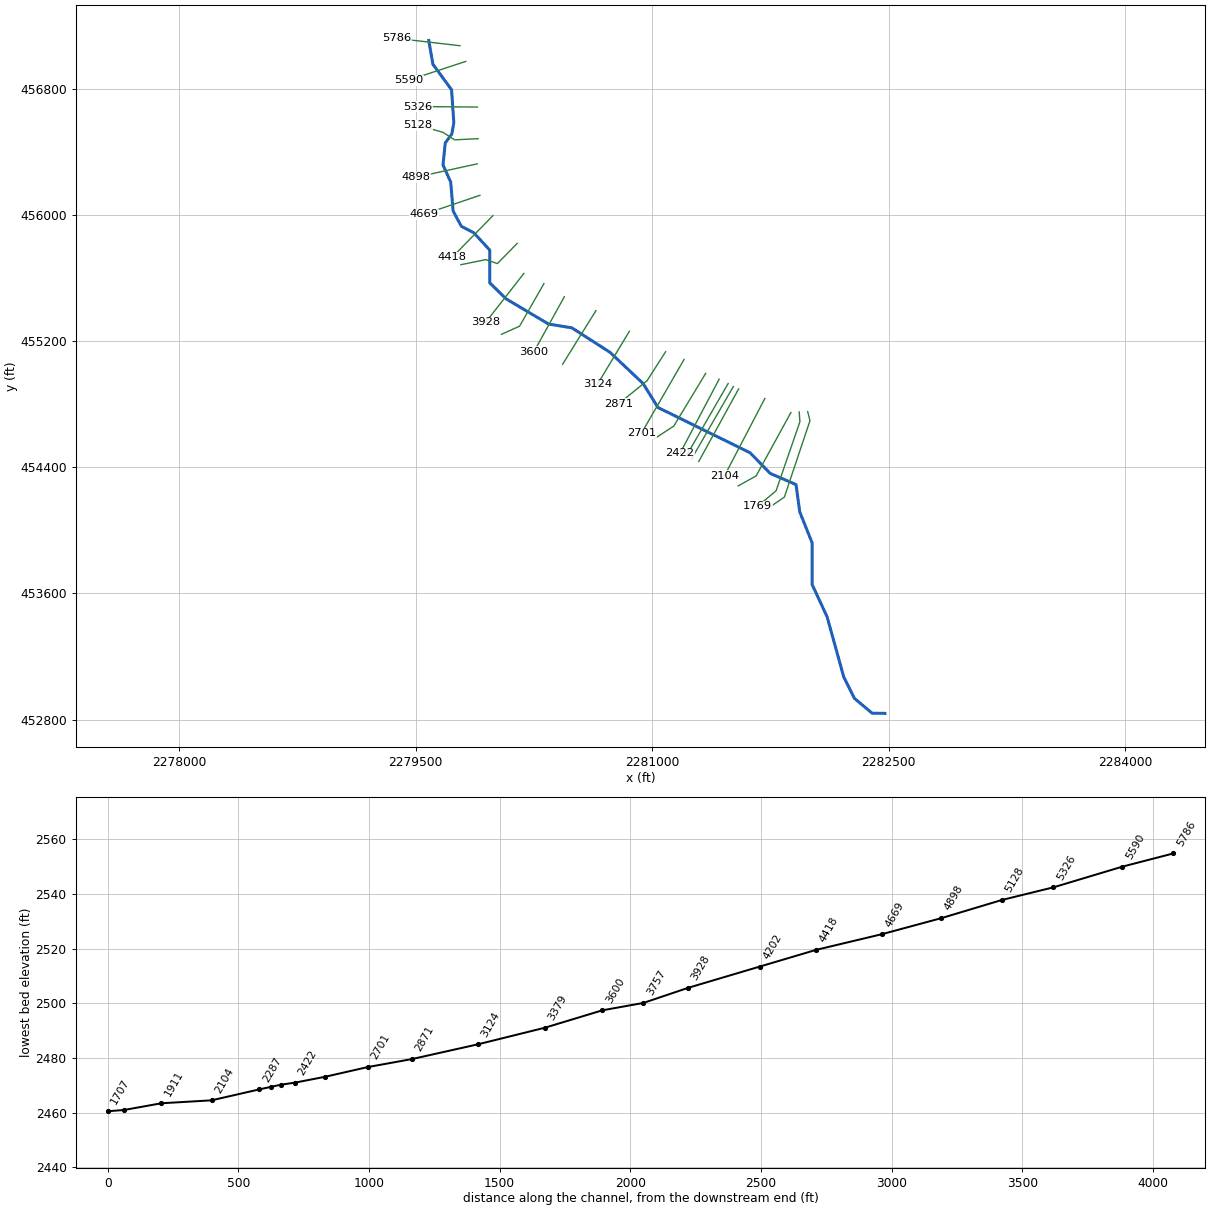
--- MILLRN.prj (project) ---

Proj Title=MILLRN
Current Plan=p01
Default Exp/Contr=0,0
English Units
Geom File=g01
Flow File=f01
Plan File=p01
Background Map Layer=Inundation Boundary (01pct Value_0)
BEGIN DESCRIPTION:
----------MODEL BY WOOD PLC 2021----------
Stream Name: Mill Run
Flood Zone: Enhanced Approximate
Pocahontas County, WV
HEC-RAS Version: RAS 6.1
Vertical Datum: NAVD88
Projection: NAD 1983 StatePlane West Virginia S FIPS 4702 (US Feet)
Terrain: 1-meter LIDAR (FEMA Region III 3DEP collected 2016-2018)
Land Use: 2019 NLCD
Hydrologic Method:
WV SIR2010-5033 regression equations
Model Notes:
Normal depth tie in to Knapp Creek
END DESCRIPTION:
DSS Export Rating Curves= 0
DSS Export Rating Curve Sorted= 0
DSS Export Volume Flow Curves= 0
DXF OffsetX= 0
DXF OffsetY= 0
DXF ScaleX= 0
DXF ScaleY= 0

--- MILLRN.p01 (plan) ---

Plan Title=Floodplain
Program Version=6.10
Short Identifier=Floodplain
Geom File=g01
Flow File=f01
Subcritical Flow
K Sum by GR= 0
Std Step Tol= 0.01
Critical Tol= 0.01
Num of Std Step Trials= 20
Max Error Tol= 0.3
Flow Tol Ratio= 0.001
Split Flow NTrial= 30
Split Flow Tol= 0.02
Split Flow Ratio= 0.02
Log Output Level= 0
Friction Slope Method= 1
Unsteady Friction Slope Method= 2
Unsteady Bridges Friction Slope Method= 1
Parabolic Critical Depth
Global Vel Dist= 0 , 0 , 0
Global Log Level= 0
CheckData=True
Encroach Param=-1 ,0,0, 0
Mapping Interval=1HOUR
Computation Time Step Use Courant=        0
Computation Time Step Use Time Series=    0
Computation Time Step Count To Double=0
Computation Time Step Max Doubling=0
Computation Time Step Max Halving=0
Computation Time Step Residence Courant=0
Run HTab= 0
Run UNet= 0
Run Sediment= 0
Run PostProcess= 0
Run WQNet= 0
Run RASMapper=-1
UNET Theta= 0
UNET Theta Warmup= 0
UNET ZTol= 0
UNET ZSATol= 0
UNET MxIter= 0
UNET Max Iter WO Improvement= 0
UNET MaxInSteps= 0
UNET DtIC= 0
UNET DtMin= 0
UNET MaxCRTS= 0
UNET WFStab= 0
UNET SFStab= 0
UNET WFX= 1
UNET SFX= 1
UNET Gravity=32.174
UNET 1D Methodology=Finite Difference
UNET DSS MLevel= 1
UNET Pardiso=0
UNET DZMax Abort= 0
UNET Use Existing IB Tables= 0
UNET Froude Reduction=False
UNET Froude Limit= 0
UNET Froude Power= 0
UNET D1 Cores= 0
UNET WindReference=Eulerian
UNET WindDragFormulation=Hsu (1988)
UNET D2 Coriolis=0
UNET D2 Cores= 0
UNET D2 Theta= 1
UNET D2 Theta Warmup= 1
UNET D2 Z Tol= 0.01
UNET D2 Volume Tol= 0.01
UNET D2 Max Iterations= 20
UNET D2 Equation= 0
UNET D2 RampUpFraction=0.1
UNET D2 TimeSlices= 1
UNET D2 Turbulence Formulation=Non-Conservative (original)
UNET D2 Eddy Viscosity=0.3
UNET D2 Transverse Eddy Viscosity=0.1
UNET D2 Smagorinsky Mixing=0
UNET D2 BCVolumeCheck=0
UNET D2 Cores=0
UNET D2 SolverType=PARDISO (Direct)
UNET D2 Minimum Iterations= 2147483647
UNET D2 Maximum Iterations= 2147483647
UNET D2 Restart Number= 10
UNET D2 Relaxation Coeff=1.3
UNET D2 SOR Precondition Iterations= 10
UNET D2 ILUT Maximum Fill= 8
UNET D2 ILUT Tolerance=1E-08
UNET D1D2 MaxIter= 0
UNET D1D2 ZTol=0.01
UNET D1D2 QTol=0.1
UNET D1D2 MinQTol=1
Write IC File= 0
Write IC File at Fixed DateTime=0
Write IC File at Sim End=0
Echo Input=False
Echo Parameters=False
Echo Output=False
Write Detailed= 0
HDF Write Warmup=0
HDF Write Time Slices=0
HDF Flush=0
HDF Compression= 1
HDF Chunk Size= 1
HDF Spatial Parts= 1
HDF Use Max Rows=0
HDF Fixed Rows= 1
Calibration Method= 0
Calibration Iterations= 20
Calibration Max Change=0.05
Calibration Tolerance=0.2
Calibration Maximum=1.5
Calibration Minimum=0.5
Calibration Optimization Method= 1
WQ AD Non Conservative
WQ ULTIMATE=-1
WQ Max Comp Step=1HOUR
WQ Output Interval=15MIN
WQ Output Selected Increments= 0
WQ Output face flow=0
WQ Output face velocity=0
WQ Output face area=0
WQ Output face dispersion=0
WQ Output cell volume=0
WQ Output cell surface area=0
WQ Output cell continuity=0
WQ Output cumulative cell continuity=0
WQ Output face conc=0
WQ Output face dconc_dx=0
WQ Output face courant=0
WQ Output face peclet=0
WQ Output face adv mass=0
WQ Output face disp mass=0
WQ Output cell mass=0
WQ Output cell source sink temp=0
WQ Output nsm pathways=0
WQ Output nsm derived pathways=0
WQ Create Restart=0
WQ Fixed Restart=0
WQ System Summary=0
WQ Write To DSS=0
Sorting and Armoring Iterations= 10
XS Update Threshold= 0.02
Bed Roughness Predictor= 0
Hydraulics Update Threshold= 0.02
Energy Slope Method= 1
Volume Change Method= 1
Sediment Retention Method= 0
Sediment TS Multiplier= 1
Warm Up Method= 0
XS Weighting Method= 0
Number of US Weighted Cross Sections= 1
Number of DS Weighted Cross Sections= 1
Upstream XS Weight=0
Main XS Weight=1
Downstream XS Weight=0
Number of DS XS's Weighted with US Boundary= 1
Upstream Boundary Weight= 1
Weight of XSs Associated with US Boundary= 0
Number of US XS's Weighted with DS Boundary= 1
Downstream Boundary Weight= 0.5
Weight of XSs Associated with DS Boundary= 0.5
Percentile Method= 0
Sediment Output Level= 3
Mass or Volume Output= 0
Output Increment Type= 1
Profile and TS Output Increment= 1
Transport Output Increment 1
XS Output Flag= 0
XS Output Increment= 10
Read HDF5 Sediment Hotstart= 0
Sediment Hotstart Type= 0
Write Gradation File= 0
Read Gradation Hotstart= 0
Write HDF5 File= 1
Write Binary Output= 1
Write DSS Sediment File= 0
DSS Sediment Output Type= 1
SV Curve= 0
Specific Gage Flag= 0
Subcell Erosion Methods= 0
Subcell Deposition Methods= 0
Advection Scheme= 1
Matrix Solver= 0
Implicit Weighting Factor= 1
Maximum Outer Loop Convergence Iterations= 5
Convergence Maximum Absolute= 0.001
Convergence RMSE= 0.0001
Grain Fractions Max Abs Error= 0.001
Max Subgrid Regions= 1
Max Subgrid Length Scale= 3.402823E+38
Initial Layer Thickness= 3.402823E+38
Min Layer Thickness= 3.402823E+38
Max Layer Thickness= 3.402823E+38
Number of Layers= 5

--- MILLRN.f01 (steady flow) ---

Flow Title=Flow
Program Version=6.10
Number of Profiles= 6
Profile Names=01pct,10pct,04pct,02pct,0_2pct,01plus
River Rch & RM=MILLRN,Main,5786
     637     338     449     540     888     942
Boundary for River Rch & Prof#=MILLRN,Main            , 1
Up Type= 0
Dn Type= 3
Dn Slope=0.01812
Boundary for River Rch & Prof#=MILLRN,Main            , 2
Up Type= 0
Dn Type= 3
Dn Slope=0.01812
Boundary for River Rch & Prof#=MILLRN,Main            , 3
Up Type= 0
Dn Type= 3
Dn Slope=0.01812
Boundary for River Rch & Prof#=MILLRN,Main            , 4
Up Type= 0
Dn Type= 3
Dn Slope=0.01812
Boundary for River Rch & Prof#=MILLRN,Main            , 5
Up Type= 0
Dn Type= 3
Dn Slope=0.01812
Boundary for River Rch & Prof#=MILLRN,Main            , 6
Up Type= 0
Dn Type= 3
Dn Slope=0.01812
DSS Import GetInterval= 0
DSS Import GetPeak= 0
DSS Import FillOption= 0

--- MILLRN.g01 (geometry) ---

Geom Title=Geometry
Program Version=6.10

River Reach=MILLRN          ,Main
Reach XY= 30
     2279583.844      457106.456      2279610.12      456955.518
     2279728.571      456793.817     2279742.824      456585.319
      2279730.28      456513.772     2279688.541      456456.457
     2279674.123      456317.027     2279722.814      456209.126
     2279738.441      456024.577      2279790.18      455928.216
     2279869.841      455886.468     2279970.567      455777.194
     2279970.661      455569.418      2280073.65       455468.27
     2280343.234      455308.116     2280491.522      455283.805
     2280733.322      455128.698     2280942.691      454931.163
     2281037.528       454778.57     2281622.571        454491.1
     2281749.249      454360.673     2281912.847      454290.025
     2281936.817      454116.005     2282015.275      453919.681
     2282015.059      453656.277      2282109.83      453452.268
     2282216.067      453068.747     2282284.113      452933.267
       2282395.7      452839.949     2282476.671      452838.841

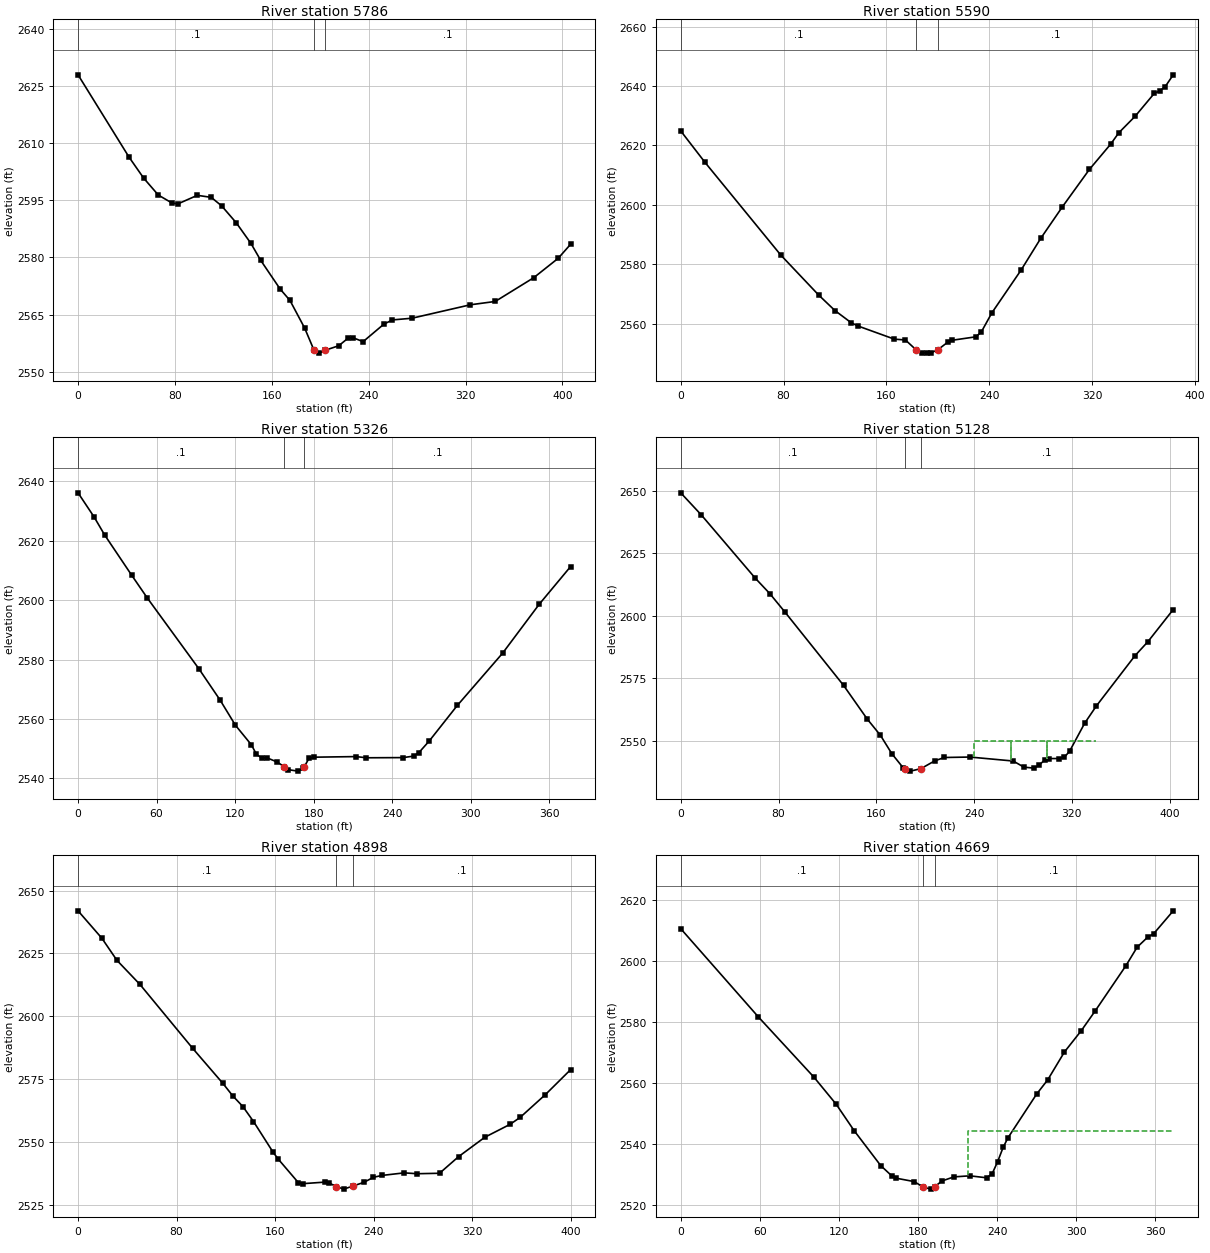
Type RM Length L Ch R = 1 ,5786    ,195.3,195.3,195.3
XS GIS Cut Line= 2
2279782.00675421457073.1072849912279378.06178325 457119.96792156
#Sta/Elev= 30
       0 2627.86    42.1 2606.28    54.2 2600.77    66.3 2596.33    77.5 2594.26
    82.4 2594.01    98.5 2596.26     110 2595.73   118.6 2593.49   130.7 2589.04
   142.8 2583.64   150.8 2579.23   166.9 2571.68     175  2568.7   187.1 2561.47
   194.82555.694   199.2 2554.88   203.62555.583   215.3 2556.82   223.3 2558.89
   227.3 2558.89   235.4 2557.89   252.5 2562.47   259.6 2563.59   275.7 2564.03
     324 2567.56   344.5 2568.43   376.3 2574.66   396.5 2579.75   406.7 2583.41
#Mann= 3 ,-1,0
       0      .1       0   194.8    .045       0   203.6      .1       0
Bank Sta=194.8,203.6
XS Rating Curve= 0 ,0
Exp/Cntr(USF)=0,0
Exp/Cntr=0.3,0.1

Type RM Length L Ch R = 1 ,5590    ,268.2,264,260.1
XS GIS Cut Line= 2
2279818.08432524456973.4252529122279454.25107841456853.659695353
#Sta/Elev= 30
       0  2624.9    18.9 2614.29    77.8 2583.08   107.3 2569.59   119.9 2564.39
   132.6 2560.27   137.9 2559.17   166.2 2554.74   174.7 2554.48   183.1 2551.13
   187.3 2550.19   191.5 2550.04     195 2550.22   199.9 2551.17   207.6 2553.71
   210.8 2554.36   229.4 2555.53   233.6 2557.06     242 2563.64   264.7 2578.04
   279.9 2588.67   296.8 2599.33   317.8 2611.93   334.4 2620.48   340.7 2624.29
   353.4 2629.85   368.4 2637.62   372.6 2638.38   376.8 2639.86     383  2643.8
#Mann= 3 ,-1,0
       0      .1       0   183.1    .045       0   199.9      .1       0
Bank Sta=183.1,199.9
XS Rating Curve= 0 ,0
Exp/Cntr(USF)=0,0
Exp/Cntr=0.3,0.1

Type RM Length L Ch R = 1 ,5326    ,202.9,198,190
XS GIS Cut Line= 2
2279892.47065637 456684.082977122279516.33051589456687.345382233
#Sta/Elev= 30
       0 2636.08    12.3 2627.94    20.3 2621.92      41 2608.35    52.9 2600.71
    92.3  2576.9   108.5 2566.38   120.2 2557.91   132.4 2551.33   136.3 2548.09
   140.3 2546.92   144.3 2546.94   152.1 2545.54  157.382543.982   160.3 2542.98
   167.9 2542.47   171.9 2543.39   172.92543.964   176.3 2546.72   180.3 2547.16
   212.3 2547.36   220.3 2546.96   248.3 2547.02   256.3 2547.52   260.3 2548.67
   268.3 2552.63   289.7 2564.56   324.3 2582.14   352.3 2598.62   376.2 2611.26
#Mann= 3 ,-1,0
       0      .1       0  157.38    .045       0   172.9      .1       0
Bank Sta=157.38,172.9
XS Rating Curve= 0 ,0
Exp/Cntr(USF)=0,0
Exp/Cntr=0.3,0.1

Type RM Length L Ch R = 1 ,5128    ,223.4,230.8,241.2
XS GIS Cut Line= 4
2279896.99823853456483.5942897232279748.22108333456476.216726078
2279672.91395244456524.3044120672279514.55892464456569.174224718
#Sta/Elev= 30
       0  2649.1    16.8 2640.28    60.9 2615.01    72.9 2608.78    84.9 2601.64
   133.2 2572.11   152.6 2558.62   163.3 2552.19   172.7 2544.79   182.2 2539.01
   183.12538.748   187.9 2537.82   196.5 2538.81   207.6 2541.88   215.5 2543.27
   236.6 2543.45     272 2541.86   280.7 2539.42     289 2539.02   293.1 2540.16
   297.9 2542.39   301.4 2542.85   309.8 2542.85   313.9 2543.42   318.1 2545.77
   330.5 2557.02     340 2563.87   371.5 2583.91   382.2  2589.6   402.9 2602.44
#Mann= 3 ,-1,0
       0      .1       0   183.1    .045       0   196.5      .1       0
#XS Ineff= 3 ,-1
     240     270    2550     270     300    2550     300     340    2550
Permanent Ineff=
       F       T       F
Bank Sta=183.1,196.5
XS Rating Curve= 0 ,0
Exp/Cntr(USF)=0,0
Exp/Cntr=0.3,0.1

Type RM Length L Ch R = 1 ,4898    ,227.1,228.3,228.8
XS GIS Cut Line= 2
2279891.02475202456323.8972602652279500.22034796456238.621719975
#Sta/Elev= 30
       0 2641.92    19.3 2631.05    31.6 2622.22    50.3 2612.62      93 2587.27
   117.6 2573.29   125.7 2568.28   133.9 2564.04   142.5  2558.1   158.5 2545.82
   162.6 2543.14     179 2533.74   183.1 2533.39   200.4 2533.99   203.5 2533.78
   209.7 2532.19   215.8  2531.2   223.1  2532.4   232.2 2533.91   239.9  2535.9
   246.7 2536.64   264.9 2537.67   275.4 2537.33   293.6 2537.51   309.1 2544.14
   330.4 2551.85   350.9 2556.98   359.1 2559.75   379.6 2568.82     400 2578.71
#Mann= 3 ,-1,0
       0      .1       0   209.7    .045       0   223.1      .1       0
Bank Sta=209.7,223.1
XS Rating Curve= 0 ,0
Exp/Cntr(USF)=0,0
Exp/Cntr=0.3,0.1

Type RM Length L Ch R = 1 ,4669    ,247,251.4,256
XS GIS Cut Line= 2
2279907.90849341456124.1785720422279554.05570971456004.413014483
#Sta/Elev= 30
       0 2610.68    58.9 2581.75   101.1 2561.98     118 2553.09   131.5  2544.5
   151.7 2533.03   160.2 2529.61   163.1 2528.92   177.1 2527.78     184 2525.96
   189.7 2525.31   192.52526.065   198.2 2527.99   207.2 2529.32   219.3 2529.67
     232 2529.03   236.2 2530.31   240.4 2534.32   244.6 2539.03   248.2 2542.11
     270 2556.48   278.4 2561.14   291.1 2570.29   303.8 2577.22   314.5 2583.79
   337.6 2598.48   346.2  2604.6   354.4 2607.97   358.7    2609   373.6 2616.53
#Mann= 3 ,-1,0
       0      .1       0     184    .045       0   192.5      .1       0
#XS Ineff= 2 , 0
                          217.94         2544.39
Permanent Ineff=
       F       F
Bank Sta=184,192.5
XS Rating Curve= 0 ,0
Exp/Cntr(USF)=0,0
Exp/Cntr=0.3,0.1

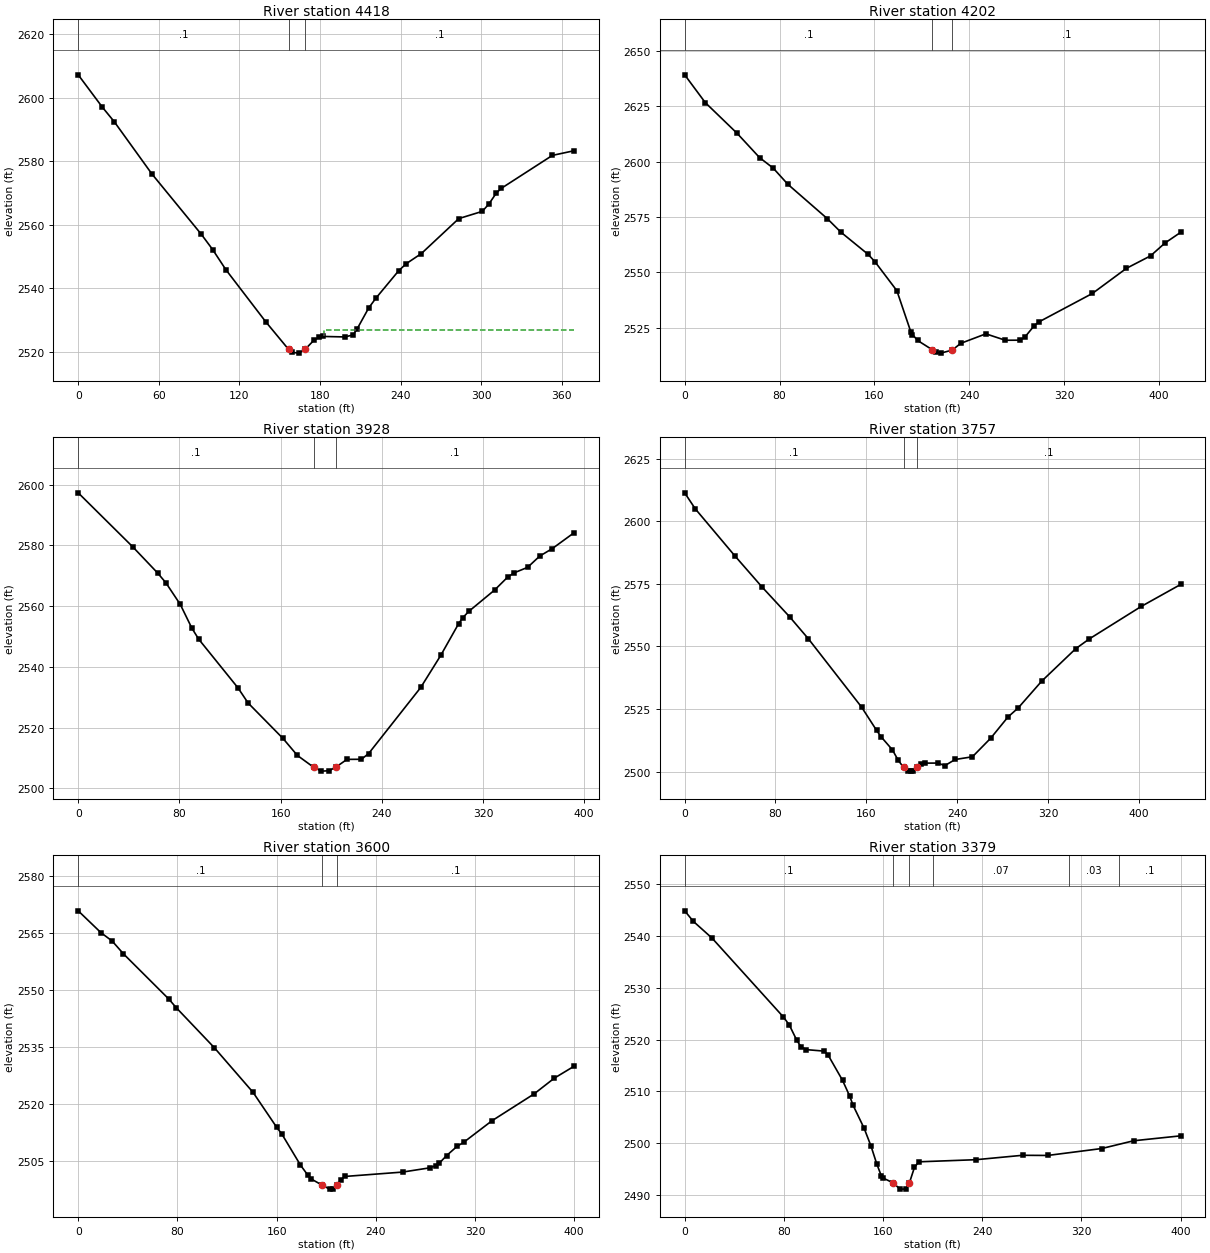
Type RM Length L Ch R = 1 ,4418    ,229,215.3,200
XS GIS Cut Line= 2
2279991.00047012455995.8518490682279732.81553957455731.742095162
#Sta/Elev= 30
       0 2607.29      18 2597.08    26.9 2592.48    54.8 2576.09    91.6 2557.07
   100.1 2552.23     110 2545.85   139.7 2529.43   156.6 2520.78   159.5 2519.81
   164.3 2519.58   169.12520.834   175.7 2523.72   179.3 2524.56   182.1 2524.84
   198.6 2524.68   204.7 2525.33   207.5 2527.06   216.3 2533.81   221.5 2536.81
   238.6 2545.53   244.3 2547.78   255.5 2550.95   283.4 2561.98   300.9 2564.26
   305.8 2566.58   311.4 2570.06     315  2571.5   353.1  2581.9   369.3 2583.37
#Mann= 3 ,-1,0
       0      .1       0   156.6    .045       0   169.1      .1       0
#XS Ineff= 2 , 0
                          182.75         2526.92
Permanent Ineff=
       F       F
Bank Sta=156.6,169.1
XS Rating Curve= 0 ,0
Exp/Cntr(USF)=0,0
Exp/Cntr=0.3,0.1

Type RM Length L Ch R = 1 ,4202    ,257.2,274.6,290.5
XS GIS Cut Line= 4
2280144.36559601455819.4520211682280019.26233518455691.497368602
2279945.76983395455716.6245455032279787.23562102455684.130879497
#Sta/Elev= 30
       0 2639.26    17.4  2626.7    44.2 2612.84    63.2 2601.84    74.7 2597.09
    87.1 2589.76   120.4 2574.22   131.8 2568.14   154.8  2558.1   160.5 2554.81
     179 2541.71   190.7 2523.23   192.2 2521.89   196.5 2519.21     2092514.967
   211.8 2513.84     216 2513.48   225.72514.844   232.9  2517.9   254.1  2522.2
   270.5  2519.3   282.7 2519.33   286.8  2520.6     295 2525.93   299.1 2527.66
     344 2540.46   372.7 2551.81     393 2557.43   405.2 2563.24   418.4 2568.06
#Mann= 3 ,-1,0
       0      .1       0     209    .045       0   225.7      .1       0
Bank Sta=209,225.7
XS Rating Curve= 0 ,0
Exp/Cntr(USF)=0,0
Exp/Cntr=0.3,0.1

Type RM Length L Ch R = 1 ,3928    ,168.7,170.9,172.6
XS GIS Cut Line= 2
2280186.83054083455628.748406347 2279945.4972354455319.691794114
#Sta/Elev= 30
       0 2597.31    43.3 2579.45    62.8 2570.91    69.3  2567.7    80.7 2560.57
    89.9 2552.72    95.3 2549.11   126.3 2533.11   134.3 2528.13   161.9 2516.45
   173.3 2510.85   186.3 2506.91   192.3 2505.69   198.2 2505.81   203.52506.939
   212.5 2509.56   223.9 2509.59   229.6 2511.47   270.8 2533.23   286.6 2543.77
   300.8 2554.26     304  2556.2     309 2558.35   329.3 2565.34   339.5 2569.55
   344.6 2570.96   355.3 2572.78   364.9 2576.49   374.8 2578.94   392.1 2584.19
#Mann= 3 ,-1,0
       0      .1       0   186.3    .045       0   203.5      .1       0
Bank Sta=186.3,203.5
XS Rating Curve= 0 ,0
Exp/Cntr(USF)=0,0
Exp/Cntr=0.3,0.1

Type RM Length L Ch R = 1 ,3757    ,157,157,157.2
XS GIS Cut Line= 3
2280314.04847359455563.9948748462280159.87872448455294.521699926
2280044.57529867455242.699935518
#Sta/Elev= 30
       0 2611.43     9.3 2605.05      44 2586.34    67.9 2573.91    92.4 2561.89
     109 2553.06   155.9 2525.73   169.1 2516.44   172.9 2513.97     183 2508.68
   188.1 2504.51   192.82501.673   196.8 2500.42   199.8 2500.17   201.4  2500.2
  204.77 2501.68   208.6 2503.04   211.6 2503.37   223.3 2503.39   229.1 2502.35
   238.3 2504.82   253.5 2505.91   269.6 2513.34   284.8 2521.81   293.8 2525.43
   314.5 2536.13   344.5 2549.12   356.6 2553.07   402.2 2566.01   436.9 2574.79
#Mann= 3 ,-1,0
       0      .1       0   192.8    .045       0  204.77      .1       0
Bank Sta=192.8,204.77
XS Rating Curve= 0 ,0
Exp/Cntr(USF)=0,0
Exp/Cntr=0.3,0.1

Type RM Length L Ch R = 1 ,3600    ,221.9,220.5,220.1
XS GIS Cut Line= 2
2280443.77039105455481.1528618132280250.12833287 455131.14892854
#Sta/Elev= 30
       0 2570.75    18.3 2565.01    27.4 2562.79    36.5 2559.42    73.1 2547.51
    79.1 2545.23   109.7 2534.74     141 2522.96     160 2513.79   164.4 2511.89
   179.2 2503.83   185.1 2501.19     188 2500.13   196.9 2498.49   202.8 2497.47
   205.7 2497.47   208.6 2498.56   211.6 2499.83   214.8  2500.8   261.6 2501.96
   283.4 2503.07   288.4 2503.64     291 2504.23   297.1  2506.3   305.8  2508.8
   310.8 2509.77   333.7 2515.47   367.6 2522.52     384 2526.69     400 2529.84
#Mann= 3 ,-1,0
       0      .1       0   196.9    .045       0   208.6      .1       0
Bank Sta=196.9,208.6
XS Rating Curve= 0 ,0
Exp/Cntr(USF)=0,0
Exp/Cntr=0.3,0.1

Type RM Length L Ch R = 1 ,3379    ,254.4,255.3,255.6
XS GIS Cut Line= 2
2280643.86280233 455392.754726052280432.70857533 455053.02852391
#Sta/Elev= 30
       0 2544.89       7 2542.85    22.1 2539.61    79.6 2524.37    84.3 2522.86
    90.3 2519.92    93.7 2518.63    97.9 2518.06   112.5 2517.77   115.6 2517.04
   127.3 2512.13   133.1 2509.07   135.8 2507.31   144.7 2502.87   150.2 2499.47
   154.9 2495.98   158.5 2493.72   159.6 2493.28   167.9 2492.33   173.8 2491.09
   178.5 2491.11   181.3 2492.33   185.3 2495.28   188.8 2496.37     235 2496.78
   272.5 2497.63   292.8  2497.6   336.4 2498.94   362.1 2500.44     400 2501.39
#Mann= 6 ,-1,0
       0      .1       0   167.9    .045       0   181.3      .1       0
     200     .07       0     310     .03       0     350      .1       0
Bank Sta=167.9,181.3
XS Rating Curve= 0 ,0
Exp/Cntr(USF)=0,0
Exp/Cntr=0.3,0.1

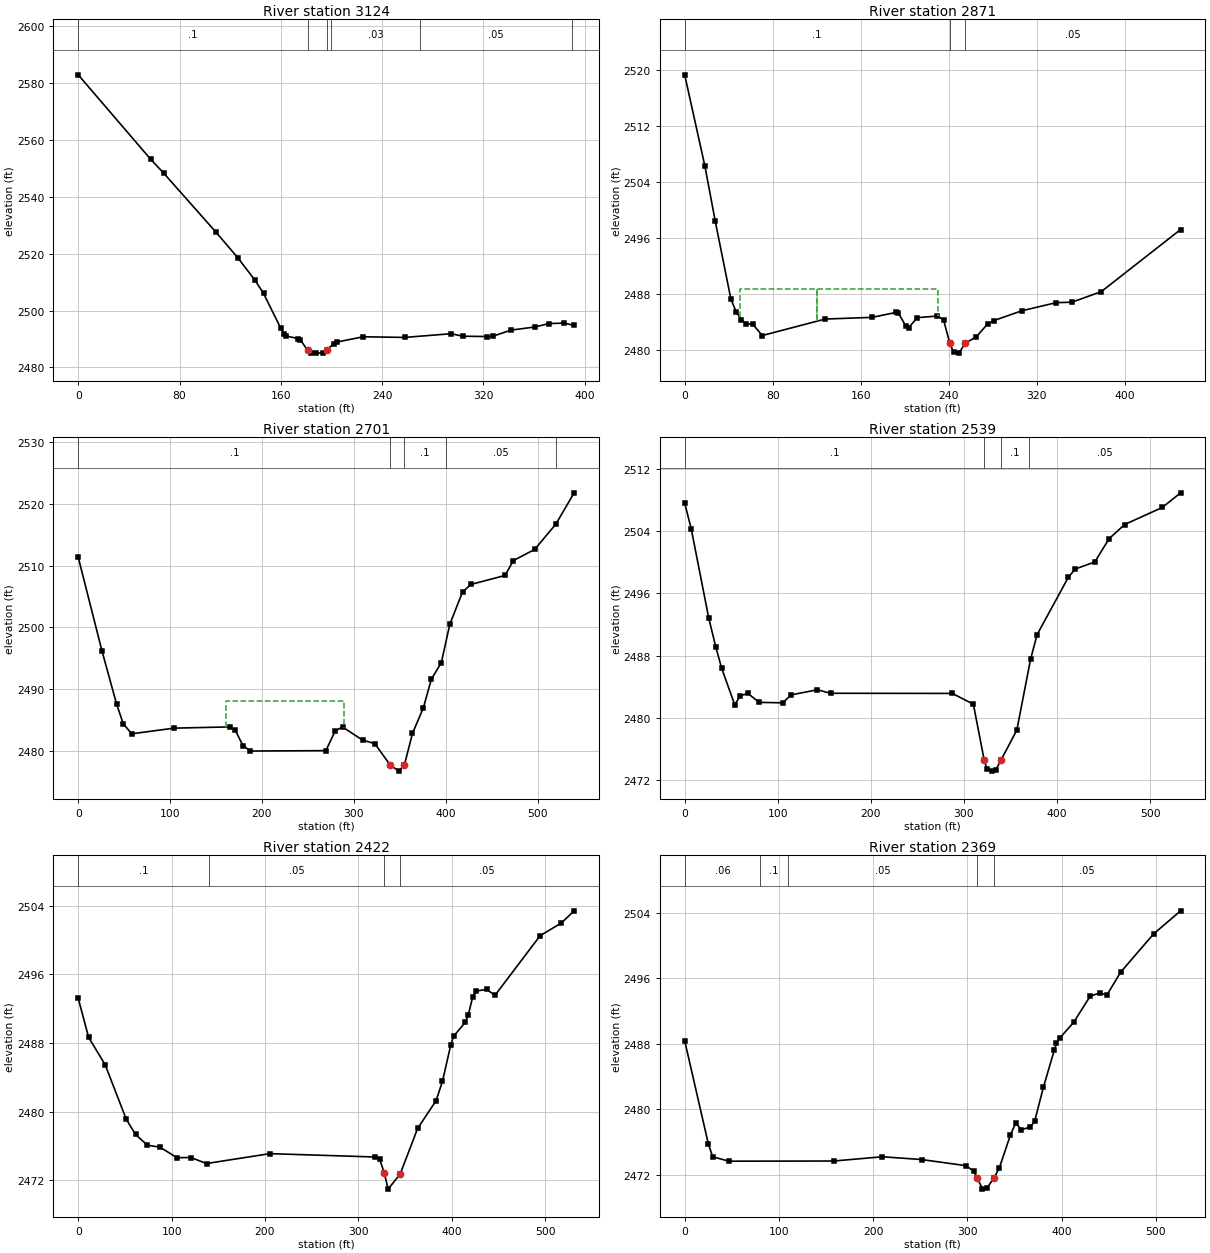
Type RM Length L Ch R = 1 ,3124    ,257.8,253.5,248.8
XS GIS Cut Line= 2
2280856.12395664455262.103697318 2280654.1007218454926.577528803
#Sta/Elev= 30
       0 2582.97    57.1 2553.32    67.7 2548.28   108.5 2527.75     126 2518.63
   139.5 2510.75   146.4 2506.04   159.8 2493.96   162.7 2491.87   164.5 2491.07
   173.8 2490.12   175.5 2489.65   181.3 2486.02   184.2 2485.18   187.8 2485.04
     193 2485.13   196.22486.016   201.7 2488.38   204.6 2488.96     225 2490.79
   257.9 2490.57   294.6 2491.87   303.7 2490.99   323.2 2490.88   327.9 2491.06
   341.9 2493.14   360.6 2494.24   372.1 2495.45   383.9 2495.61   391.7 2494.78
#Mann= 6 ,-1,0
       0      .1       0   181.3    .045       0   196.2      .1       0
     200     .03       0     270     .05       0     390      .1       0
Bank Sta=181.3,196.2
XS Rating Curve= 0 ,0
Exp/Cntr(USF)=0,0
Exp/Cntr=0.3,0.1

Type RM Length L Ch R = 1 ,2871    ,165.9,169.3,175.1
XS GIS Cut Line= 3
2281086.19276326455132.5786861512280968.29824924454948.611422504
2280788.21761792454802.214938052
#Sta/Elev= 30
       0 2519.31    18.4 2506.27    27.8 2498.41      42 2487.32    46.8 2485.51
    51.5 2484.37      56  2483.8    61.8 2483.75    70.5 2482.13   127.6 2484.48
   170.3 2484.72   192.1 2485.43   194.1 2485.36   200.8 2483.51   203.6 2483.25
   211.3 2484.68   229.6 2484.91   235.2 2484.37   240.9 2481.01   244.4 2479.72
   249.3 2479.62   254.7    2481   265.1 2481.97   275.4 2483.81   280.7 2484.25
   306.3 2485.66   337.6 2486.82   351.8 2486.88   378.5 2488.39   450.6 2497.25
#Mann= 3 ,-1,0
       0      .1       0   240.9    .045       0   254.7     .05       0
#XS Ineff= 2 ,-1
      50     120 2488.78     120     230 2488.78
Permanent Ineff=
       T       F
Bank Sta=240.9,254.7
XS Rating Curve= 0 ,0
Exp/Cntr(USF)=0,0
Exp/Cntr=0.3,0.1

Type RM Length L Ch R = 1 ,2701    ,161.9,162.5,161.9
XS GIS Cut Line= 2
2281202.89370671455083.5711568082280933.09307974454615.934661727
#Sta/Elev= 30
       0 2511.37    25.9 2496.16    41.8 2487.56    48.9 2484.41    58.2 2482.74
   104.4 2483.66   164.8 2483.86   170.7 2483.38   179.4 2480.83   187.5 2479.95
   269.6 2480.01   279.8 2483.22   287.8 2483.84   309.6 2481.72   322.9 2481.15
   339.9 2477.62   349.3 2476.69   355.2 2477.76   363.9 2482.81   375.7 2486.93
   384.4 2491.57   395.3 2494.28   404.5 2500.48   418.4 2505.75   427.6 2506.96
   464.6 2508.41   473.8 2510.83   496.9 2512.63     520 2516.74   539.9 2521.81
#Mann= 5 ,-1,0
       0      .1       0   339.9    .045       0   355.2      .1       0
     400     .05       0     520      .1       0
#XS Ineff= 1 ,-1
  160.56  289.69 2488.01
Permanent Ineff=
       T
Bank Sta=339.9,355.2
XS Rating Curve= 0 ,0
Exp/Cntr(USF)=0,0
Exp/Cntr=0.3,0.1

Type RM Length L Ch R = 1 ,2539    ,116.4,116.5,116.5
XS GIS Cut Line= 3
2281340.11940886454995.2510104712281138.01452767 454661.00063004
2281018.82446953454583.267983429
#Sta/Elev= 30
       0 2507.62     7.1 2504.27    25.8 2492.86    33.5 2489.07    39.8 2486.36
    53.8 2481.67    59.7 2482.83    67.9 2483.14    80.1 2481.99   105.3 2481.93
   114.6 2482.96   142.7 2483.61   156.7 2483.16   287.6 2483.14   310.2 2481.76
   321.9 2474.53   324.8 2473.44   330.6 2473.15   334.3 2473.32     340 2474.59
   356.9 2478.42   371.7 2487.55   378.7  2490.7   412.2 2498.06   419.6 2499.13
   440.6 2500.04   456.2 2503.05   472.7 2504.85   513.2 2507.05   532.9 2508.93
#Mann= 4 ,-1,0
       0      .1       0   321.9    .045       0     340      .1       0
     370     .05       0
Bank Sta=321.9,340
XS Rating Curve= 0 ,0
Exp/Cntr(USF)=0,0
Exp/Cntr=0.3,0.1

Type RM Length L Ch R = 1 ,2422    ,55.3,52.8,54.2
BEGIN DESCRIPTION:
structure xs 4
END DESCRIPTION:
XS GIS Cut Line= 2
2281425.66241469454958.7007779232281177.78695262454489.002830278
#Sta/Elev= 30
       0 2493.21    11.1 2488.67    28.9 2485.46    51.5 2479.11    61.4 2477.35
    74.1 2476.11    87.7 2475.87   105.7 2474.65   120.6 2474.67   137.4 2473.97
   205.2 2475.12   318.3 2474.73   322.8 2474.48   327.9 2472.81   331.9 2470.99
   344.8 2472.75   363.5 2478.06   383.2 2481.28   390.1 2483.54   398.9 2487.75
   401.9 2488.78   414.6 2490.41   417.8 2491.31   422.3 2493.31   425.6 2494.04
   437.4 2494.24   446.3 2493.55   494.7  2500.5   517.4 2501.97   531.1 2503.39
#Mann= 4 ,-1,0
       0      .1       0     140     .05       0   327.9    .045       0
   344.8     .05       0
Bank Sta=327.9,344.8
XS Rating Curve= 0 ,0
Exp/Cntr(USF)=0,0
Exp/Cntr=0.5,0.3

Type RM Length L Ch R = 1 ,2369    ,38.5,38.8,38.6
BEGIN DESCRIPTION:
structure xs 3; 18.4 ft between structure and xs
END DESCRIPTION:
XS GIS Cut Line= 2
   2281482.51086454930.9024864512281219.29203402 454475.02344016
#Sta/Elev= 30
       0 2488.36    25.1 2475.78    29.7  2474.2    46.9 2473.66   158.2 2473.68
   209.8  2474.2   251.4 2473.86   298.7 2473.11   306.8 2472.43   310.4 2471.66
   316.1 2470.25   320.7 2470.36     328 2471.56   333.9 2472.81   345.6  2476.8
   351.4 2478.34   357.3 2477.49   366.9 2477.84   371.5 2478.55   380.7 2482.66
   392.4 2487.24   394.6 2488.03   398.3  2488.7   413.1 2490.64   430.5 2493.81
   440.8 2494.19   448.1 2493.92   462.7 2496.72   497.8  2501.4   526.4 2504.21
#Mann= 5 ,-1,0
       0     .06       0      80      .1       0     110     .05       0
   310.4    .045       0     328     .05       0
#XS Ineff= 2 , 0
             292  2471.6     346          2471.3
Permanent Ineff=
       F       F
Bank Sta=310.4,328
XS Rating Curve= 0 ,0
Exp/Cntr(USF)=0,0
Exp/Cntr=0.5,0.3

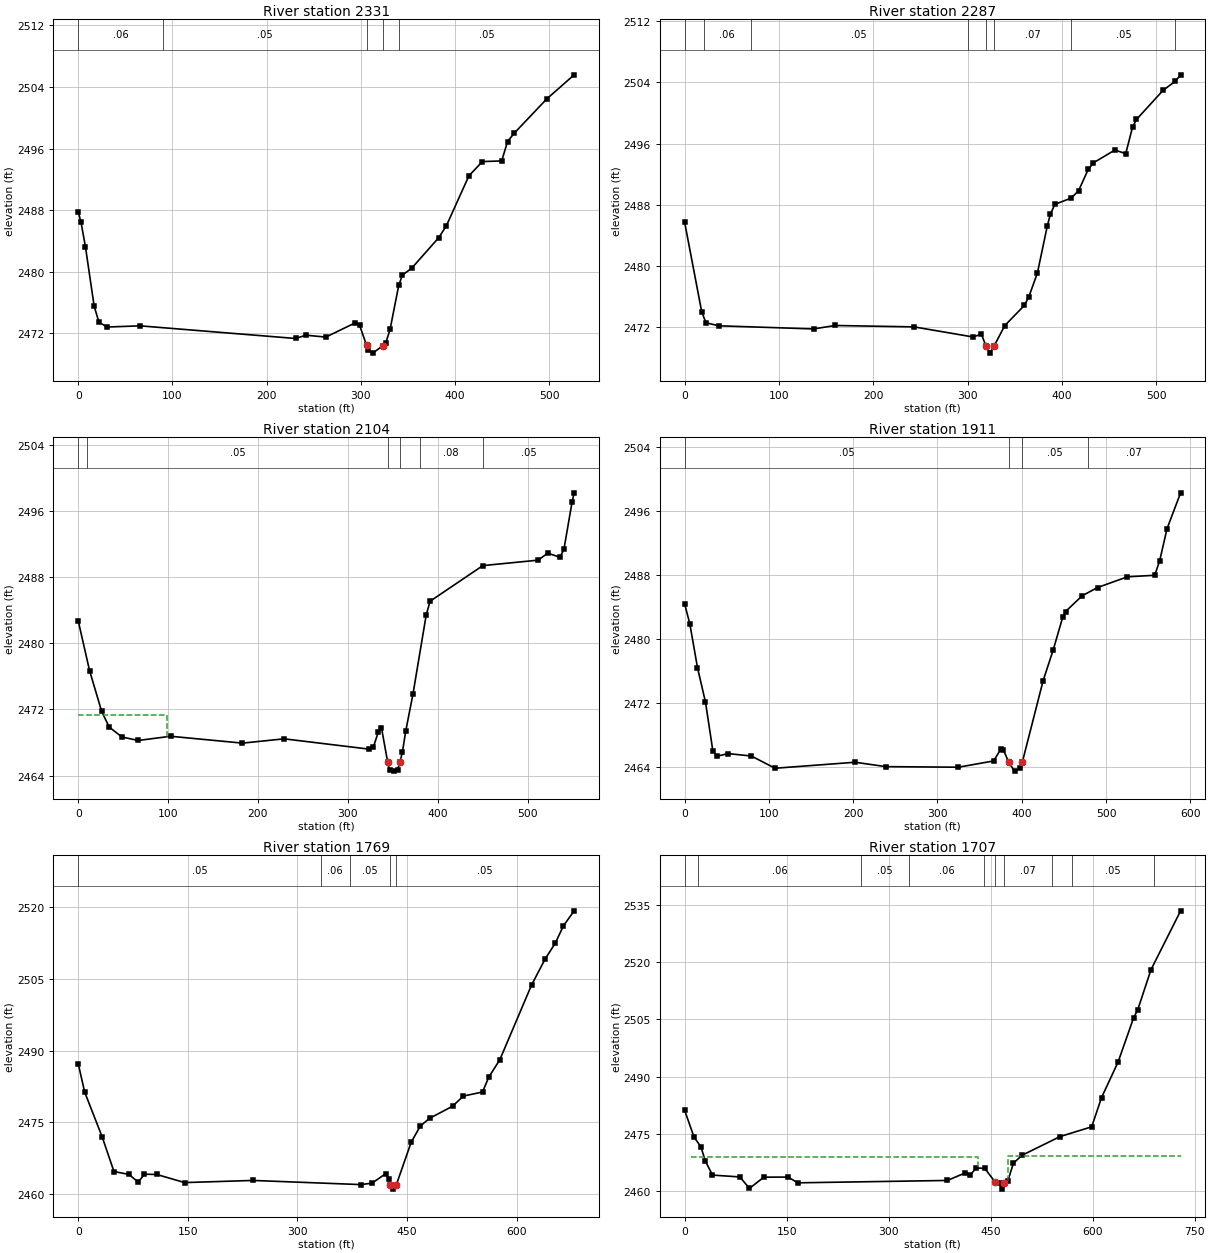
Type RM Length L Ch R = 1 ,2331    ,44.5,43.5,43.8
BEGIN DESCRIPTION:
structure xs 2; 7.1 ft between structure and xs
END DESCRIPTION:
XS GIS Cut Line= 2
2281515.55944738454911.804797579 2281252.3406214454455.925751289
#Sta/Elev= 30
       0 2487.82       3 2486.42     7.7 2483.24    16.9 2475.56      22 2473.46
    30.7 2472.84    65.9 2472.99   230.8 2471.35   241.6 2471.78   262.8 2471.53
   294.3  2473.4   298.6 2473.09     306 2470.49   307.9 2469.81   312.5 2469.45
   323.6 2470.42   326.4 2470.76     331 2472.52   340.2 2478.25   344.1 2479.57
   354.1 2480.49   382.8 2484.46   390.8 2485.99   414.7 2492.47     429 2494.32
   449.5  2494.4   455.7 2496.92   462.7 2497.99   497.3 2502.45   526.4 2505.58
#Mann= 5 ,-1,0
       0     .06       0      90     .05       0     306    .045       0
   323.6     .07       0     340     .05       0
#XS Ineff= 2 , 0
             299  2471.6     330          2471.3
Permanent Ineff=
       F       F
Bank Sta=306,323.6
XS Rating Curve= 0 ,0
Exp/Cntr(USF)=0,0
Exp/Cntr=0.5,0.3

Type RM Length L Ch R = 1 ,2287    ,182.9,183.3,183.4
BEGIN DESCRIPTION:
structure xs 1
END DESCRIPTION:
XS GIS Cut Line= 2
2281549.22796035454896.9180050952281296.14190298454436.152506534
#Sta/Elev= 30
       0 2485.66      18 2473.98    22.5 2472.52    36.2 2472.12   136.6 2471.71
   159.4 2472.16   243.1 2471.98   305.5 2470.66   314.6 2471.02   319.2 2469.51
   323.7 2468.54   328.22469.521   339.3 2472.15     360 2474.78   364.8 2475.92
   373.9 2479.04   384.4 2485.21   387.6 2486.74   392.4 2488.03     410 2488.87
   417.6 2489.84   427.7  2492.6   433.3 2493.48   456.1 2495.15   467.5 2494.67
   474.8 2498.17   478.9 2499.15   507.2 2502.98     520 2504.15   525.7    2505
#Mann= 8 ,-1,0
       0      .1       0      20     .06       0      70     .05       0
     300     .07       0   319.2    .045       0   328.2     .07       0
     410     .05       0     520      .1       0
Bank Sta=319.2,328.2
XS Rating Curve= 0 ,0
Exp/Cntr(USF)=0,0
Exp/Cntr=0.3,0.1

Type RM Length L Ch R = 1 ,2104    ,192.6,192.4,191.3
XS GIS Cut Line= 2
2281715.57968045454836.3602162582281460.26769358454347.111974398
#Sta/Elev= 30
       0 2482.73    12.6 2476.71    26.1 2471.76    34.5 2469.86    48.7 2468.66
    66.8 2468.24   102.7 2468.75   182.8 2467.92   229.2 2468.44   323.9 2467.19
   328.4 2467.42     334 2469.28   337.5 2469.76   344.3 2465.68   346.5 2464.63
     351 2464.53   355.5 2464.72     358 2465.62   360.7 2466.79   364.5 2469.39
   372.5 2473.84   387.3 2483.46   391.6  2485.1   450.3 2489.41   511.9 2490.07
   522.5 2490.92     536 2490.42   540.5 2491.37   549.5 2497.05   551.9 2498.22
#Mann= 6 ,-1,0
       0      .1       0      10     .05       0   344.3    .045       0
     358     .05       0     380     .08       0     450     .05       0
#XS Ineff= 2 , 0
            98.7 2471.35
Permanent Ineff=
       F       F
Bank Sta=344.3,358
XS Rating Curve= 0 ,0
Exp/Cntr(USF)=0,0
Exp/Cntr=0.3,0.1

Type RM Length L Ch R = 1 ,1911    ,141.1,142.9,143.9
XS GIS Cut Line= 3
2281880.36130281454746.5065413132281660.11880408454344.887867153
2281546.11092238454281.406205753
#Sta/Elev= 30
       0 2484.34     6.1 2481.87    15.2 2476.39    24.7 2472.07    33.4 2466.02
      38 2465.31    51.7 2465.64    79.1 2465.34   107.2 2463.81   202.2 2464.56
   238.7 2464.01   324.8 2463.94   366.5 2464.72   375.6 2466.26   378.2 2466.11
   384.52464.566   391.4 2463.45   398.4 2463.83  400.66 2464.58   425.4 2474.78
   437.2 2478.57   448.6  2482.7   451.9  2483.4   471.7 2485.38     490 2486.41
   525.4 2487.75   557.8 2487.94   563.7 2489.78   572.4 2493.78   588.5 2498.25
#Mann= 4 ,-1,0
       0     .05       0   384.5    .045       0  400.66     .05       0
  478.04     .07       0
Bank Sta=384.5,400.66
XS Rating Curve= 0 ,0
Exp/Cntr(USF)=0,0
Exp/Cntr=0.3,0.1

Type RM Length L Ch R = 1 ,1769    ,62,61.9,62.8
BEGIN DESCRIPTION:
structure xs 4
END DESCRIPTION:
XS GIS Cut Line= 4
2281933.23086031454749.9933252172281937.71142737454688.385528119
2281786.49228904 454250.410097842281668.87740367454151.837622483
#Sta/Elev= 30
       0 2487.29     8.8 2481.34    32.9 2471.89    48.9 2464.68    69.4 2464.07
    82.1 2462.45    90.7 2464.12   107.5 2464.06   145.6 2462.36     239 2462.81
   386.8 2461.94   402.1 2462.24   420.6 2464.22   424.9 2463.16   427.2 2461.88
   430.4 2460.99  435.232461.869   455.6 2470.82   468.1  2474.2   480.7 2475.82
   512.2 2478.36     527 2480.49   553.2 2481.34   561.7 2484.43   576.9 2488.11
   620.4 2503.78   639.1 2509.27   652.6 2512.47     664 2516.17   678.6  2519.3
#Mann= 5 ,-1,0
       0     .05       0  331.77     .06       0  371.77     .05       0
   427.2    .045       0  435.23     .05       0
Bank Sta=427.2,435.23
XS Rating Curve= 0 ,0
Exp/Cntr(USF)=0,0
Exp/Cntr=0.5,0.3

Type RM Length L Ch R = 1 ,1707    ,44.2,44.8,45.1
BEGIN DESCRIPTION:
structure xs 3; 5.7 ft between structure and xs
END DESCRIPTION:
XS GIS Cut Line= 4
2281986.96760655454752.8885433142282001.48464383454694.820394194
  2281839.015602454210.279596513 2281708.2081126454120.788893463
#Sta/Elev= 30
       0 2481.13    13.9 2474.09    23.8 2471.65    30.4 2467.88    40.9 2464.21
    81.1 2463.73    95.3 2460.73   116.4 2463.67   152.1 2463.69   166.4 2462.19
   386.4 2462.81   411.8 2464.72   420.2 2464.28   428.9  2466.1   441.4 2465.95
   457.1 2462.28   462.4 2462.05   466.6 2460.54   469.8 2462.24     475 2462.54
   483.5 2467.32   496.1 2469.39   551.9 2474.28   598.6 2476.85   613.1  2484.5
   637.4 2493.78   660.1 2505.29   666.4 2507.52   685.8 2517.95   729.4 2533.36
#Mann= 10 ,-1,0
       0      .1       0      20     .06       0  259.86     .05       0
  329.86     .06       0  439.86     .07       0   457.1    .045       0
   469.8     .07       0  539.86     .06       0  569.86     .05       0
  690.91     .08       0
#XS Ineff= 4 ,-1
       0    9.01  2462.8    9.01  431.77    2469  431.77     451  2462.8
     475   729.4  2469.3
Permanent Ineff=
       F       F       F       F
Bank Sta=457.1,469.8
XS Rating Curve= 0 ,0
Exp/Cntr(USF)=0,0
Exp/Cntr=0.5,0.3