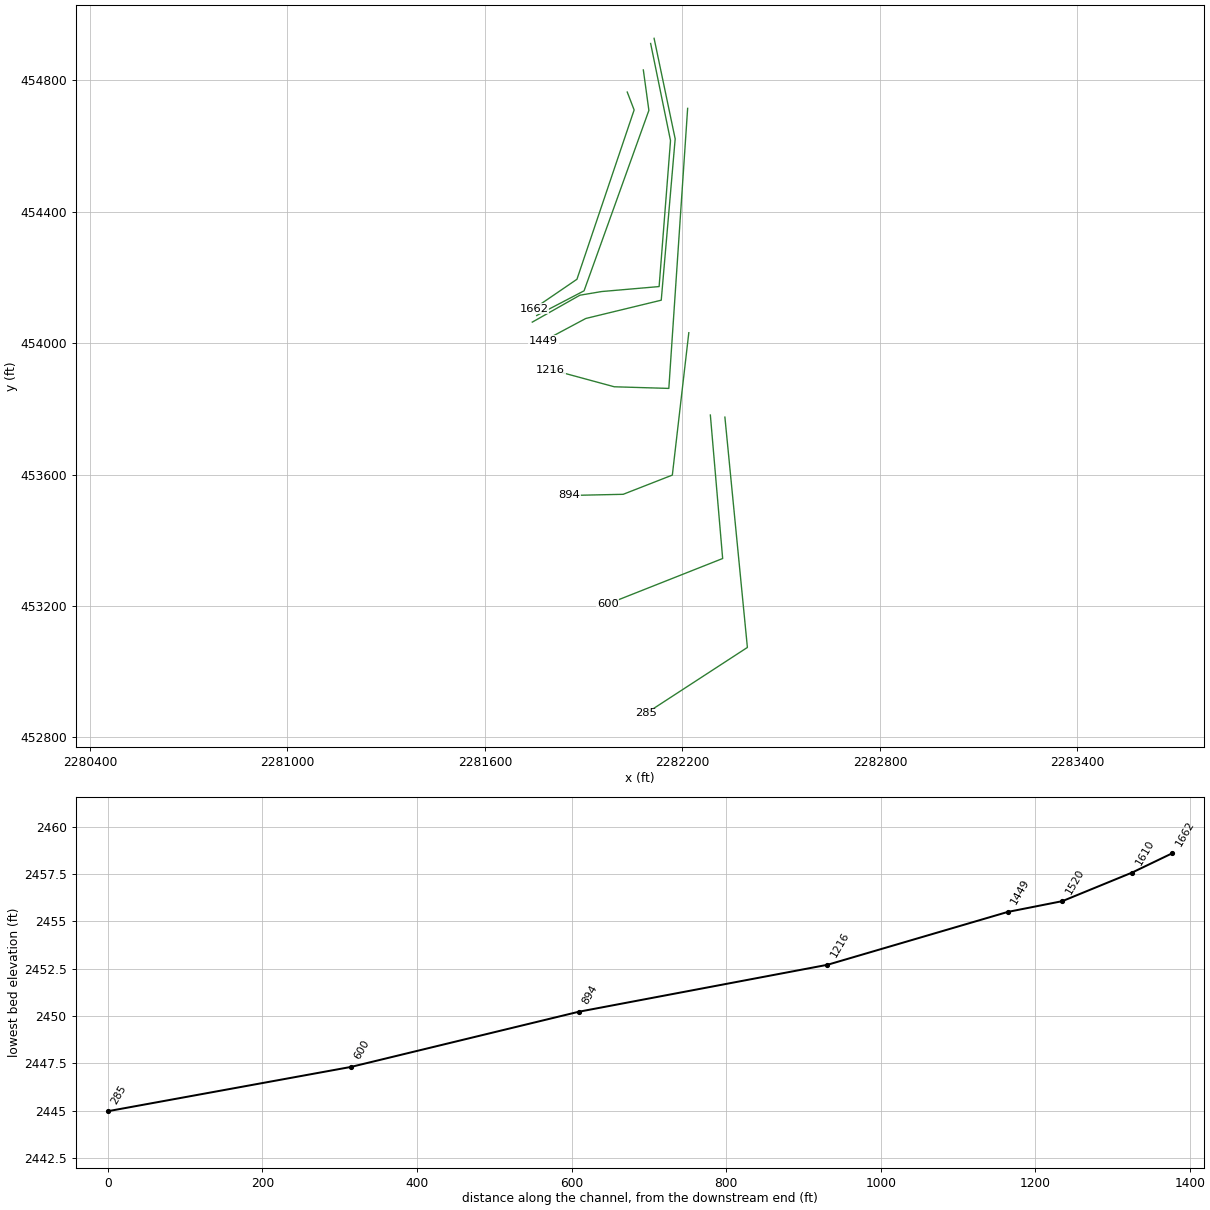
HEC-RAS study MILLRN.prj: MILLRN

--- MILLRN.g01 (geometry) --- (continued)

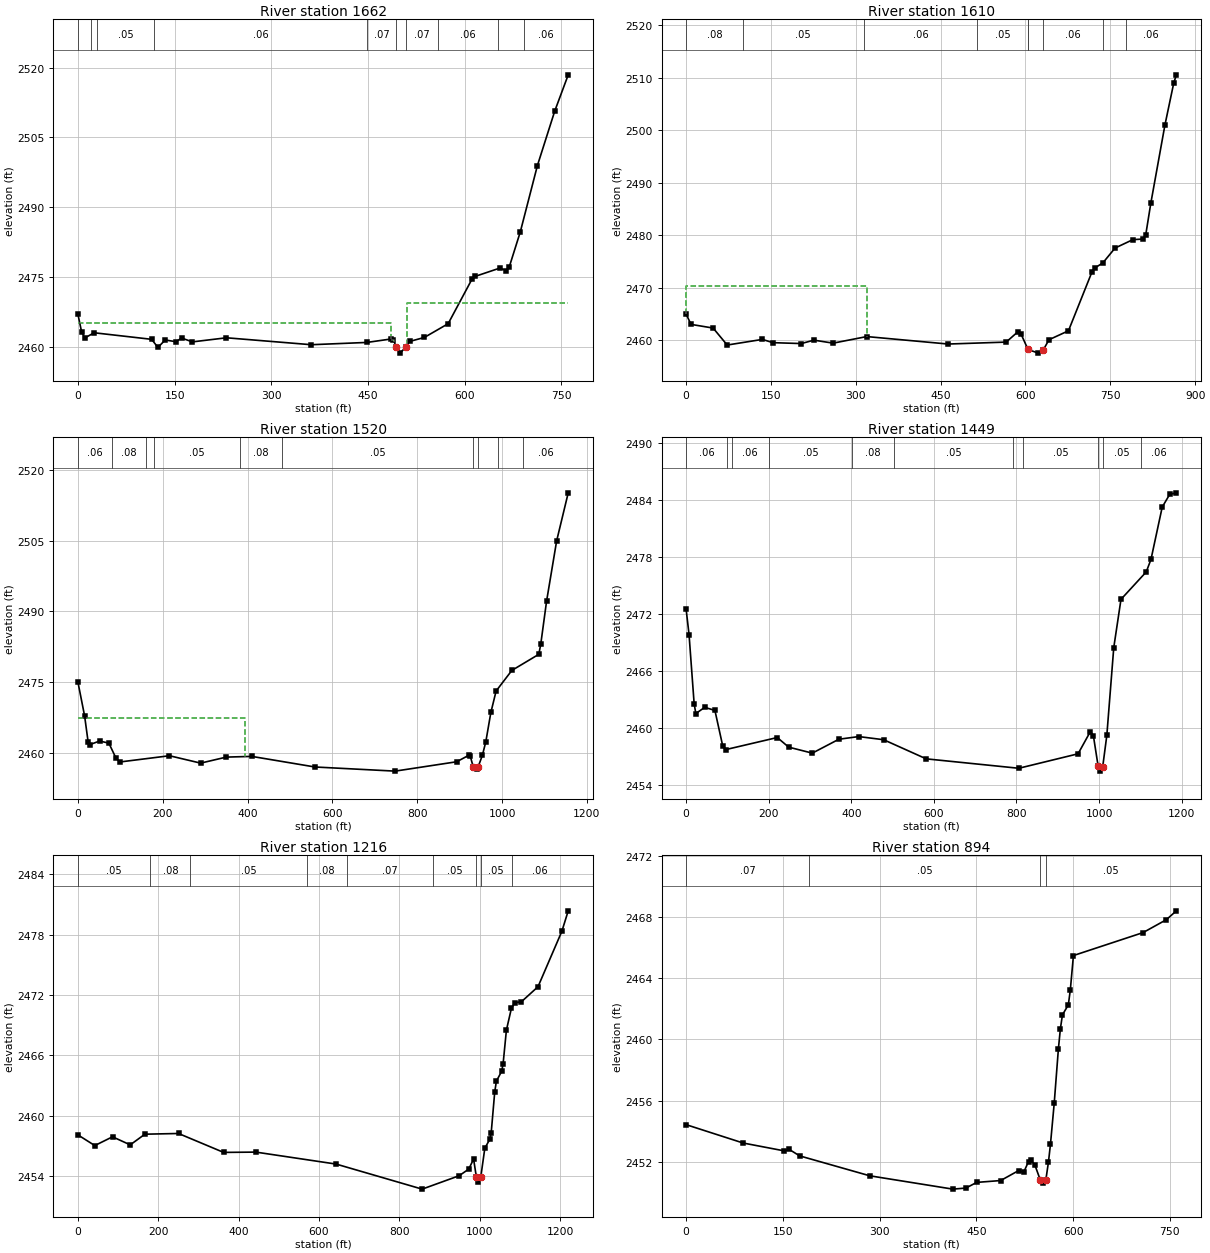
Type RM Length L Ch R = 1 ,1662    ,44.2,51.5,57.9
BEGIN DESCRIPTION:
structure xs 2; 11.4 ft between structure and xs
END DESCRIPTION:
XS GIS Cut Line= 4
2282032.33334805454764.6836361042282053.20158914454710.244746304
2281879.46507205   454194.7834062281748.65758265 454105.29270295
#Sta/Elev= 30
       0 2466.93     5.7 2463.14    10.7 2461.85    25.2 2462.96   114.3 2461.55
   124.1 2459.81   135.4 2461.41   152.3 2461.03   160.7 2461.83   177.6    2461
   230.4 2461.88   362.1 2460.39   448.3 2460.88   486.2 2461.63   489.3 2461.48
   494.2 2459.82   499.8 2458.58508.63182459.869   514.6 2461.09   537.4 2461.95
   574.4 2464.91   611.1 2474.42   615.9 2475.07   654.7 2476.88   664.4 2476.33
   669.2 2477.12   686.4 2484.69   712.9 2498.94   739.7 2510.62   760.7 2518.45
#Mann= 10 ,-1,0
       0      .1       0      20     .08       0      30     .05       0
   118.3     .06       0   448.3     .07       0   494.2    .045       0
508.6318     .07       0   558.3     .06       0  652.25     .05       0
  692.25     .06       0
#XS Ineff= 3 ,-1
       0  485.25    2465  485.25     491  2461.5     511   760.7  2469.3
Permanent Ineff=
       F       F       F
Bank Sta=494.2,508.6318
XS Rating Curve= 0 ,0
Exp/Cntr(USF)=0,0
Exp/Cntr=0.5,0.3

Type RM Length L Ch R = 1 ,1610    ,109.3,90.3,70.2
BEGIN DESCRIPTION:
structure xs 1
END DESCRIPTION:
XS GIS Cut Line= 4
2282081.17063989454832.0124525862282098.01271332454708.935762124
2281901.09000858454159.6250593952281757.28461235454084.483501004
#Sta/Elev= 30
       0 2465.02     8.7 2463.04    47.8 2462.34    72.7 2459.11   134.9 2460.18
   153.6 2459.56   203.7 2459.39   225.9 2460.04     260 2459.47   319.4 2460.72
   463.3  2459.3   565.9 2459.67   587.1 2461.68   591.9 2461.27604.52622458.262
   622.8 2457.57 631.3262458.145   641.6 2460.12     676 2461.82   717.8 2473.08
   722.3 2473.75   736.9 2474.75   758.4 2477.57     790 2479.17   808.1 2479.28
   812.6 2480.05   821.6 2486.09   846.6    2501   862.2 2508.99   866.8 2510.53
#Mann= 9 ,-1,0
       0     .08       0     100     .05       0  314.22     .06       0
  514.22     .05       0  604.22     .07       0604.5262    .045       0
 631.326     .06       0  737.77     .05       0  777.77     .06       0
#XS Ineff= 2 , 0
          320.56  2470.4
Permanent Ineff=
       F       F
Bank Sta=604.5262,631.326
XS Rating Curve= 0 ,0
Exp/Cntr(USF)=0,0
Exp/Cntr=0.3,0.1

Type RM Length L Ch R = 1 ,1520    ,69.7,70.7,71.3
XS GIS Cut Line= 6
2282103.38384913454912.5900653482282163.75499802454616.810571012
2282129.10577197454172.5805004972281954.51355385 454157.43833131
2281888.42518969454146.2369136562281743.80066329454064.362370245
#Sta/Elev= 30
       0 2474.97    15.7 2467.81    23.9 2462.35    27.3 2461.66      51 2462.46
    72.9 2462.01    89.2 2458.92    98.5    2458   215.8 2459.33   289.3 2457.76
   349.8 2459.04   409.8 2459.19   558.7 2456.94   747.8 2456.06   892.9 2458.05
     921  2459.4   925.1 2459.19  931.88 2456.98   939.9 2456.48  943.53 2456.97
   953.5 2459.42   961.6  2462.3   973.5 2468.52   985.9 2473.09    1023 2477.46
  1086.5 2480.88  1091.1 2483.01  1104.9  2492.2  1128.6 2504.99  1155.9  2515.2
#Mann= 10 ,-1,0
       0     .06       0      80     .08       0     160     .06       0
     180     .05       0  381.88     .08       0  481.88     .05       0
  931.88    .045       0  943.53     .06       0  989.74     .05       0
 1049.74     .06       0
#XS Ineff= 2 , 0
          394.82 2467.42
Permanent Ineff=
       F       F
Bank Sta=931.88,943.53
XS Rating Curve= 0 ,0
Exp/Cntr(USF)=0,0
Exp/Cntr=0.3,0.1

Type RM Length L Ch R = 1 ,1449    ,234.8,233.2,230.2
XS GIS Cut Line= 5
2282113.86759599454928.2694857292282177.90190594454622.320586054
2282135.58349252454131.1230889712281906.27218502454075.414692232
2281778.01331811454006.750854392
#Sta/Elev= 30
       0 2472.55     7.2 2469.83    19.5 2462.58    23.6 2461.54    45.1 2462.19
    69.8 2461.87      89 2458.08    95.8 2457.75   220.8 2459.02   248.4 2458.01
   305.6 2457.38   369.9 2458.84   418.1 2459.12   478.3 2458.79   581.4 2456.78
   805.6 2455.79   949.1 2457.31   978.9 2459.65   986.1 2459.23  997.78 2455.98
  1002.6 2455.49  1008.8 2455.97  1018.7 2459.24  1035.5 2468.47    1053 2473.54
  1114.1 2476.42  1125.6 2477.73  1152.8 2483.23    1171 2484.57  1187.1 2484.73
#Mann= 11 ,-1,0
       0     .06       0     100     .08       0     110     .06       0
     200     .05       0  402.58     .08       0  502.58     .05       0
  792.58     .08       0   815.6     .05       0  997.78    .045       0
  1008.8     .05       0 1101.58     .06       0
Bank Sta=997.78,1008.8
XS Rating Curve= 0 ,0
Exp/Cntr(USF)=0,0
Exp/Cntr=0.3,0.1

Type RM Length L Ch R = 1 ,1216    ,317.7,321.9,326.2
XS GIS Cut Line= 4
2282215.76940408454715.0598919782282158.60845709453862.555111565
2281992.93408025453867.5132645642281799.59597294453920.062493881
#Sta/Elev= 30
       0 2458.09      42 2457.03    86.1  2457.9   130.2  2457.1   166.7 2458.16
   250.4 2458.23   362.7 2456.35   442.9 2456.38   642.7 2455.19   856.9  2452.7
   948.9 2454.03   972.9 2454.69   984.9 2455.69  991.93 2453.89   996.9 2453.38
  1002.7 2453.87  1012.9 2456.77  1025.1 2457.64  1028.7 2458.27  1037.5 2462.34
  1041.7 2463.44  1054.7  2464.4  1058.3 2465.12  1066.6  2468.5    1079 2470.66
  1087.5 2471.23  1103.9 2471.32  1145.3 2472.82  1204.7 2478.33  1220.5 2480.36
#Mann= 9 ,-1,0
       0     .05       0     180     .08       0     280     .05       0
     570     .08       0     670     .07       0  884.42     .05       0
  991.93    .045       0  1002.7     .05       0 1080.17     .06       0
Bank Sta=991.93,1002.7
XS Rating Curve= 0 ,0
Exp/Cntr(USF)=0,0
Exp/Cntr=0.3,0.1

Type RM Length L Ch R = 1 ,894     ,294.2,294.4,294.3
XS GIS Cut Line= 4
2282219.31898495 454032.092339022282169.26763939 453598.65445968
2282019.93808519453540.1712877912281856.57674599453536.617223425
#Sta/Elev= 30
       0 2454.43    88.5 2453.23   151.9 2452.72     160 2452.81   176.1 2452.39
   284.8 2451.09   413.6 2450.22   433.8 2450.29   450.6 2450.66   487.7 2450.78
   515.5 2451.43   523.4 2451.32   530.9 2452.02     534 2452.12   540.6 2451.81
   549.2 2450.81   553.5 2450.64   557.8 2450.84   561.8 2451.99   564.9 2453.15
   570.7 2455.82   577.2 2459.38   580.3  2460.7   583.5  2461.6   592.6 2462.25
   595.7 2463.23   600.5 2465.47   708.5 2466.97   744.5 2467.81   760.1 2468.39
#Mann= 4 ,-1,0
       0     .07       0     190     .05       0   549.2    .045       0
   557.8     .05       0
Bank Sta=549.2,557.8
XS Rating Curve= 0 ,0
Exp/Cntr(USF)=0,0
Exp/Cntr=0.3,0.1

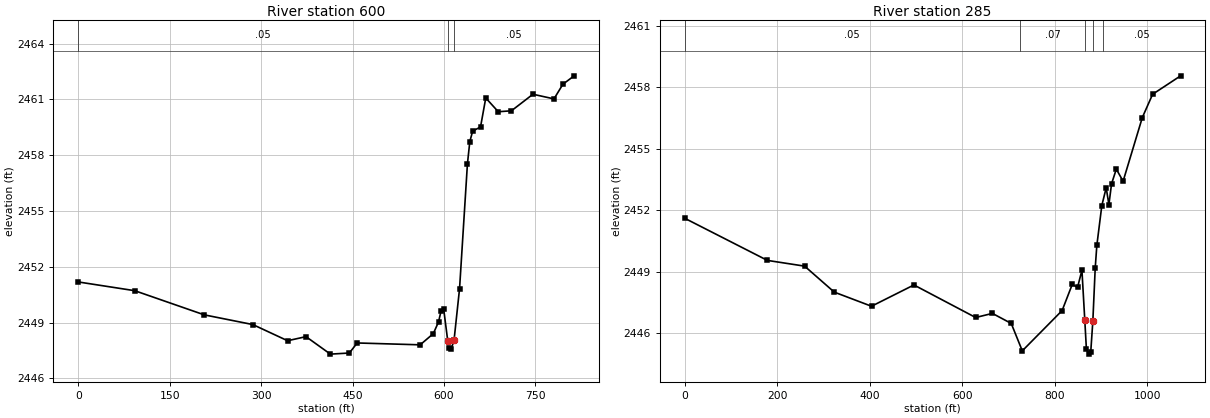
Type RM Length L Ch R = 1 ,600     ,313.3,314.8,318
XS GIS Cut Line= 3
2282284.77650899453781.5339106172282322.14184439453344.727814082
2281973.40893651453206.401080516
#Sta/Elev= 30
       0 2451.19    92.7 2450.72   206.9 2449.42   286.4  2448.9   343.5 2448.03
   373.7 2448.25   413.7 2447.31   444.8 2447.37   457.7 2447.91     561 2447.81
   582.5 2448.41   591.1 2449.04   595.4 2449.65   599.6 2449.72606.25552448.015
   608.3 2447.64   612.1 2447.59616.65542448.087   625.6 2450.83   638.5 2457.53
   642.4 2458.73   647.1  2459.3     660 2459.52   668.6 2461.08   689.1 2460.34
   710.7 2460.39     746 2461.28   780.5 2461.03   795.2 2461.82   813.6 2462.27
#Mann= 3 ,-1,0
       0     .05       0606.2555    .045       0616.6554     .05       0
Bank Sta=606.2555,616.6554
XS Rating Curve= 0 ,0
Exp/Cntr(USF)=0,0
Exp/Cntr=0.3,0.1

Type RM Length L Ch R = 1 ,285     ,,,
XS GIS Cut Line= 3
2282328.94365861453775.1297281282282397.28340278453073.959095051
2282089.50842677452873.270094897
#Sta/Elev= 30
       0 2451.61   178.8 2449.55   259.2 2449.27   323.3    2448   403.8 2447.31
   495.5 2448.35   628.9 2446.76   665.1 2446.96   705.8 2446.47   729.7 2445.13
   815.8  2447.1   837.7 2448.38   849.1 2448.23   858.6 2449.07   864.8 2446.62
   868.2 2445.24     873 2444.97   877.7 2445.09   882.2 2446.59   887.3 2449.17
   890.8 2450.28   901.6 2452.23     911  2453.1   916.9 2452.28   922.6 2453.29
   932.9 2454.01   947.6 2453.42   989.1 2456.53  1011.4 2457.67  1071.9 2458.57
#Mann= 5 ,-1,0
       0     .05       0  724.49     .07       0   864.8    .045       0
   882.2     .07       0  904.49     .05       0
Bank Sta=864.8,882.2
XS Rating Curve= 0 ,0
Exp/Cntr(USF)=0,0
Exp/Cntr=0.3,0.1
LCMann Table=0

Chan Stop Cuts=-1
Use User Specified Reach Order=0
Composite Channel Slope=5